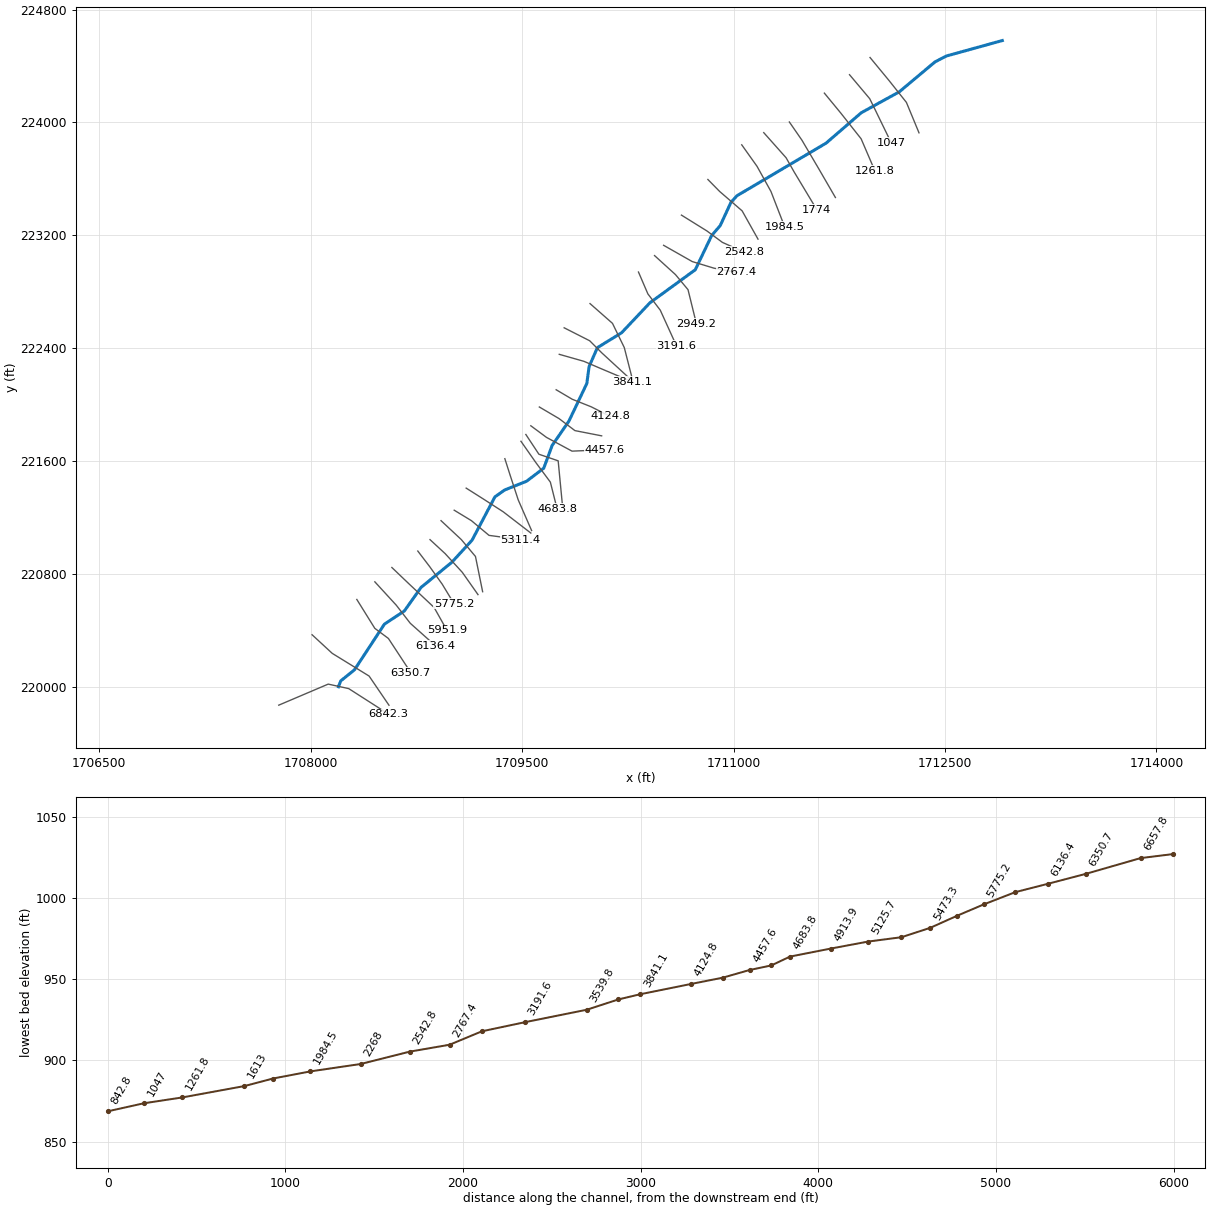
--- sklltcrk.prj (project) ---

Proj Title=sklltcrk
Current Plan=p01
Default Exp/Contr=0,0
English Units
Geom File=g01
Flow File=f01
Plan File=p01
BEGIN DESCRIPTION:
END DESCRIPTION:
DSS Export Rating Curves= 0
DSS Export Rating Curve Sorted= 0
DSS Export Volume Flow Curves= 0
DXF OffsetX= 0
DXF OffsetY= 0
DXF ScaleX= 0
DXF ScaleY= 0

--- sklltcrk.p01 (plan) ---

Plan Title=Floodplain
Program Version=4.00
Geom File=g01
Flow File=f01
K Sum by GR=0
Std Step Tol=0.01
Critical Tol=0.01
Num of Std Step Trials=20
Max Error Tol=0.3
Flow Tol Ratio=0.001
Split Flow NTrial=30
Split Flow Tol=0.02
Split Flow Ratio=0.02
Log Output Level=0
Friction Slope Method=1
Unsteady Friction Slope Method=2
Unsteady Bridges Friction Slope Method=1
Global Log Level=0
CheckData=False
Run HTab=0
Run UNet=0
Run PostProcess=0
UNET Theta=0
UNET Theta Warmup=0
UNET ZTol=0
UNET ZSATol=0
UNET MxIter=0
UNET MaxInSteps=0
UNET DtIC=0
UNET DtMin=0
UNET MaxCRTS=0
UNET WFStab=0
UNET SFStab=0
UNET WFX=0
UNET SFX=0
UNET DSS MLevel=0
UNET DZMax Abort=0
UNET Convert EG Bridges=0
UNET Use Existing IB Tables=0
UNET Froude Limit=0
UNET Froude Power=0
Write IC File=0
Echo Input=False
Echo Output=False
Write Detailed=0

--- sklltcrk.f01 (steady flow) ---

Flow Title=NFF Regression Equation
Program Version=4.00
Number of Profiles= 1
Profile Names=P100yr
River Rch & RM=sklltcrk,Main            ,6842.3
     379
River Rch & RM=sklltcrk,Main            ,5622.7
     399
River Rch & RM=sklltcrk,Main            ,4683.8
     440
River Rch & RM=sklltcrk,Main            ,4457.6
     493
River Rch & RM=sklltcrk,Main            ,2949.2
     538
River Rch & RM=sklltcrk,Main            ,267
     591
Boundary for River Rch & Prof#=sklltcrk,Main            , 1
Up Type= 0
Dn Type= 3
Dn Slope=0.018
DSS Import GetInterval= 0
DSS Import GetPeak= 0
DSS Import FillOption= 0

--- sklltcrk.g01 (geometry) ---

Geom Title=USGS 10m DEM
Program Version=4.00

River Reach=sklltcrk        ,Main
Reach XY= 30
     1708196.747      219998.763     1708213.129      220040.297
      1708310.74      220119.075     1708522.914      220442.754
      1708664.57      220536.246     1708782.846      220703.218
     1709002.209      220882.339     1709144.706       221038.09
     1709306.922      221345.165     1709375.189      221393.647
     1709531.592      221455.991     1709653.367      221548.642
     1709712.857       221709.47     1709832.005      221882.482
     1709958.801       222148.88     1709975.111      222269.042
     1710033.756       222403.08     1710205.672      222508.742
     1710406.881      222721.562     1710728.241      222955.327
     1710844.697      223198.326     1710905.152      223268.436
     1710981.029      223432.711     1711024.221      223480.339
     1711655.748      223852.643     1711905.377      224068.185
      1712175.83      224217.114     1712428.867      224429.148
     1712509.243      224470.747     1712906.594      224580.564

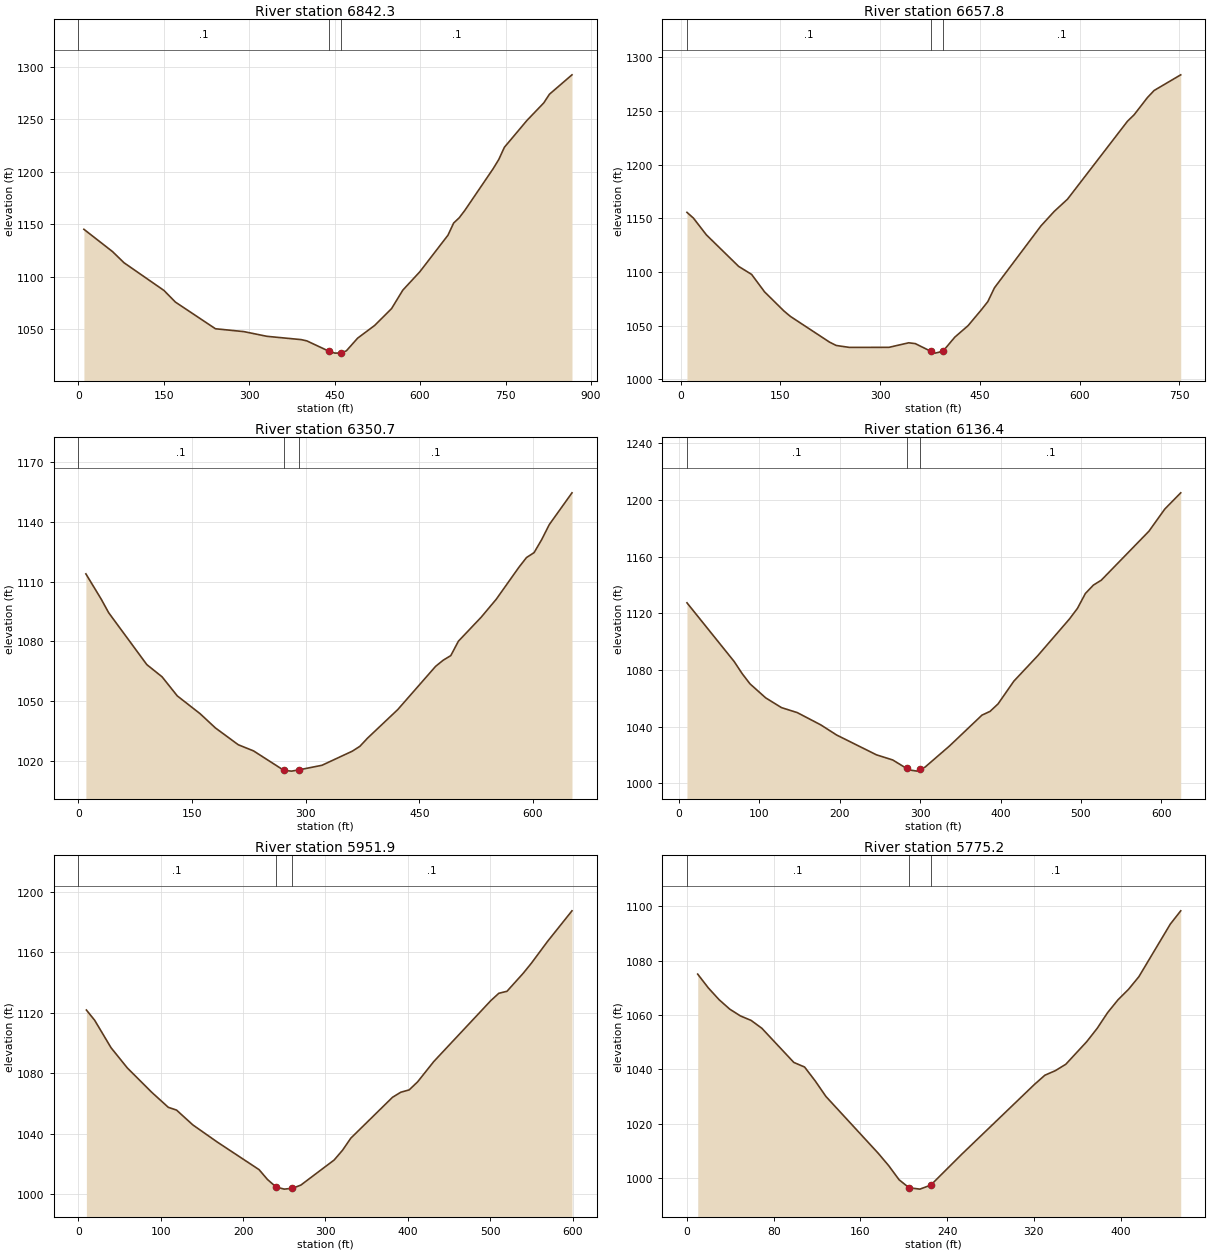
Type RM Length L Ch R = 1 ,6842.3  ,193.2,184.5,175.8
XS GIS Cut Line= 4
     1707773.272      219868.297     1708124.223      220017.556
      1708269.59      219985.703     1708553.023      219804.233
#Sta/Elev= 30
      10 1145.09    60.2 1123.82    80.3 1113.21   150.5 1086.75   170.6 1075.63
   240.9  1050.2     291 1047.45   331.2 1042.99   391.3 1039.84   401.2 1038.65
   440.8 1028.59   450.8 1026.95   460.8 1027.12   470.7 1029.15   490.5 1041.26
   520.3 1053.35     550 1069.43   569.8 1087.07   599.5  1104.5     649 1139.46
   658.9 1151.01   668.8 1156.11   678.7 1163.22   728.2 1202.82   738.1 1211.61
     748 1223.32   787.6 1248.94   817.2 1265.71   827.1 1273.96   866.7 1292.48
#Mann= 3 , 0 , 0
       0      .1       0   440.8    .045       0   460.8      .1       0
Bank Sta=440.8,460.8
XS Rating Curve= 0 ,0
Exp/Cntr=0.3,0.1

Type RM Length L Ch R = 1 ,6657.8  ,309.3,307.1,304.9
XS GIS Cut Line= 4
     1708009.809      220367.507     1708152.581      220235.718
     1708414.328      220074.643     1708555.269      219867.807
#Sta/Elev= 30
     9.7 1155.61    19.4 1150.27    38.9 1134.64    87.4 1105.27   106.9 1097.79
   126.3 1081.58   155.4 1063.77   165.2 1058.67     224 1034.72     234 1031.61
   253.8  1029.8   313.3 1029.86     343 1034.09   352.9 1033.34  376.66 1026.03
   382.7 1024.47  394.39 1026.16   412.4  1039.4   432.2 1050.04   452.1 1064.74
     462 1072.53   471.9 1085.32   541.7 1142.92   561.7 1156.48   581.7 1167.88
   671.8 1240.47   681.8 1246.49   701.9 1262.59   711.9 1269.15   751.9 1283.74
#Mann= 3 , 0 , 0
     9.7      .1       0  376.66    .045       0  394.39      .1       0
Bank Sta=376.66,394.39
XS Rating Curve= 0 ,0
Exp/Cntr=0.3,0.1

Type RM Length L Ch R = 1 ,6350.7  ,221.2,214.3,207.5
XS GIS Cut Line= 4
     1708327.155      220617.788     1708454.797      220412.947
     1708551.322      220341.133     1708710.395      220098.876
#Sta/Elev= 30
    10.1 1113.85    30.2 1101.24    40.2 1094.33    90.5 1068.29   110.6 1062.17
   130.7 1052.59   160.9 1043.61     181  1036.5   211.2 1028.05   231.3 1024.97
   271.5 1015.16   281.5 1014.81   291.5 1015.47   321.6 1017.74   361.7 1024.84
   371.7 1027.29   381.7 1031.36   421.6 1045.71   471.6 1067.44   481.6 1070.51
   491.6 1072.82   501.6 1080.03   531.6 1092.06   551.5 1101.08   581.5 1117.18
   591.5 1122.05   601.5 1124.52   611.5 1131.04   621.5 1138.56   651.5 1154.54
#Mann= 3 , 0 , 0
       0      .1       0   271.5    .045       0   291.5      .1       0
Bank Sta=271.5,291.5
XS Rating Curve= 0 ,0
Exp/Cntr=0.3,0.1

Type RM Length L Ch R = 1 ,6136.4  ,180.6,184.5,188.5
XS GIS Cut Line= 4
     1708455.054      220742.719     1708607.435      220576.611
     1708706.277       220448.94     1708883.368      220291.068
#Sta/Elev= 30
     9.8 1127.45    68.6 1085.96    78.4 1077.53    88.2 1070.27   107.8 1060.34
   127.4 1053.48     147 1049.97   176.4 1041.27     196 1034.15   245.6 1020.15
   265.8 1016.54  282.97 1010.59     286 1009.54   296.1 1008.66  300.13 1009.92
   306.1 1011.53   336.4  1026.4   376.8 1048.17   386.9 1050.84   396.8 1056.08
   416.5 1072.16   446.2 1090.11   485.7 1116.05   495.6 1123.52   505.5 1134.04
   515.4 1139.92   525.3 1143.43   584.6 1178.01   604.3 1193.64   624.1 1205.07
#Mann= 3 , 0 , 0
     9.8      .1       0  282.97    .045       0  300.13      .1       0
Bank Sta=282.97,300.13
XS Rating Curve= 0 ,0
Exp/Cntr=0.3,0.1

Type RM Length L Ch R = 1 ,5951.9  ,181.6,176.7,171.7
XS GIS Cut Line= 4
     1708575.861      220844.307      1708698.04      220727.619
     1708875.131       220561.51     1708967.109      220398.147
#Sta/Elev= 30
     9.9 1121.76    19.9 1115.04    39.8 1096.88    59.6  1083.5    89.4 1067.34
   109.3 1057.52   119.3 1055.69   139.1  1045.9   168.9 1034.53   219.5 1016.35
   229.7 1009.85   239.9 1004.99   249.9  1003.5   259.9 1004.05   270.1 1006.14
   310.6 1022.74   320.7 1029.15   330.8 1037.15   381.4 1064.14   391.5 1067.49
   401.6 1069.02   411.8 1074.29   431.5 1087.76   500.6 1127.91   510.4 1132.81
   520.3 1134.12     540 1146.01   549.9 1152.65   569.6  1167.1   599.2 1187.25
#Mann= 3 , 0 , 0
       0      .1       0   239.9    .045       0   259.9      .1       0
Bank Sta=239.9,259.9
XS Rating Curve= 0 ,0
Exp/Cntr=0.3,0.1

Type RM Length L Ch R = 1 ,5775.2  ,149.5,152.5,155.6
XS GIS Cut Line= 4
     1708759.816      220960.995     1708843.557      220851.171
     1708932.789      220726.246     1709017.903       220586.22
#Sta/Elev= 30
     9.9 1075.03    19.7 1069.97    29.6 1065.65    39.5 1062.15    49.3 1059.67
    59.2 1058.01    69.1 1055.12    98.6 1042.56   108.5 1040.88   118.4 1035.72
   128.2 1030.05   176.5 1009.15   186.1 1004.62   195.7  999.43   204.9  996.49
   214.9  995.99   224.9  997.46   253.2  1008.7   320.5 1034.46   330.2 1037.87
   339.8 1039.53   349.5  1041.9   368.7 1050.16   378.4 1055.08     388 1060.85
   397.7 1065.62   407.3 1069.42   416.9 1074.09   445.9 1093.42   455.5  1098.3
#Mann= 3 , 0 , 0
       0      .1       0   204.9    .045       0   224.9      .1       0
Bank Sta=204.9,224.9
XS Rating Curve= 0 ,0
Exp/Cntr=0.3,0.1

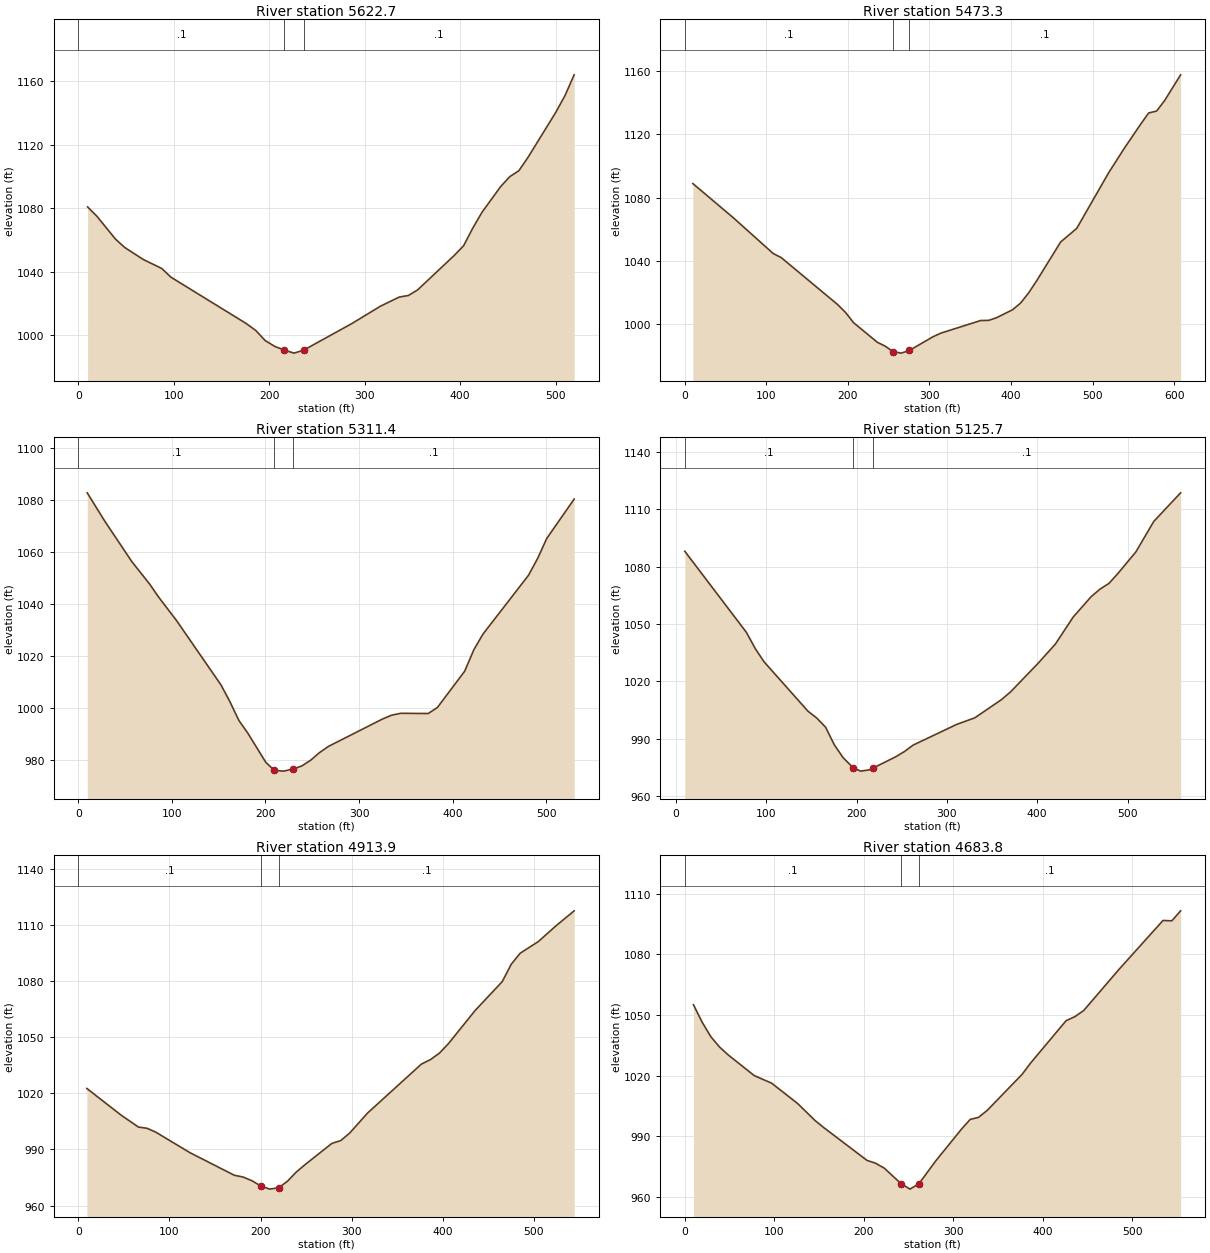
Type RM Length L Ch R = 1 ,5622.7  ,150.6,149.4,148.3
XS GIS Cut Line= 4
     1708846.303       221041.99     1708953.381      220943.148
      1709075.56      220809.987     1709186.757      220652.115
#Sta/Elev= 30
     9.7 1080.94    19.4 1075.09    38.9  1060.7    48.6 1055.39      68 1047.85
    87.4 1042.18    97.1 1036.67   175.8 1007.57   185.9 1003.16   195.9  996.74
     206  993.08     216  990.78     226  988.89     236  990.74   286.3  1007.4
   316.4 1018.39   336.1 1024.16   345.8 1025.17   355.4 1028.65     394 1050.46
   403.7 1056.51   413.3  1067.6     423 1077.61   442.3 1093.59     452 1099.95
   461.6 1103.74   471.3 1112.27   500.2 1140.42   509.9 1151.03   519.5 1164.08
#Mann= 3 , 0 , 0
       0      .1       0     216    .045       0     236      .1       0
Bank Sta=216,236
XS Rating Curve= 0 ,0
Exp/Cntr=0.3,0.1

Type RM Length L Ch R = 1 ,5473.3  ,157.4,161.9,166.3
XS GIS Cut Line= 4
     1708924.552      221176.525     1709068.696       221041.99
     1709168.911      220922.556     1709219.704      220672.707
#Sta/Elev= 30
     9.9 1088.89    59.2 1067.38   108.4 1044.61   118.3    1042   187.3 1012.35
   197.2 1007.27   206.9 1000.85   236.1  988.43   245.9  985.91   255.4  982.47
   265.4  981.55   275.4  983.25   304.4  991.93   314.1  994.23   362.9  1002.2
   372.7 1002.29   382.5 1004.01   402.1 1009.05   411.9 1013.33   421.7 1019.72
   431.5 1027.39   460.9 1051.91   480.6 1060.52   519.8 1095.78   539.4 1111.57
     559 1126.48   568.8 1133.58   578.6  1134.8   588.4 1141.45     608 1157.73
#Mann= 3 , 0 , 0
       0      .1       0   255.4    .045       0   275.4      .1       0
Bank Sta=255.4,275.4
XS Rating Curve= 0 ,0
Exp/Cntr=0.3,0.1

Type RM Length L Ch R = 1 ,5311.4  ,182.6,185.7,188.8
XS GIS Cut Line= 4
     1709017.903      221250.656     1709140.082      221176.525
     1709265.007      221072.192     1709487.172      221041.984
#Sta/Elev= 30
     9.5 1082.74    28.6 1071.66    57.2  1056.3    76.2 1047.68    85.7 1042.73
   104.8 1033.73   152.5 1008.89   162.1 1002.39   171.6  995.24   181.2  990.34
   200.4  979.15   209.5  976.06   219.5  975.78   229.5  976.59   238.7  977.75
   248.2  979.94   257.8  982.91   267.4   985.3   325.2  995.83   334.9  997.29
   344.7  998.01   373.9  997.92   383.7 1000.22   412.9 1014.18   422.7 1022.43
   432.4 1028.42   481.1 1051.05   490.9 1057.54   500.6  1065.2   529.9 1080.34
#Mann= 3 , 0 , 0
       0      .1       0   209.5    .045       0   229.5      .1       0
Bank Sta=209.5,229.5
XS Rating Curve= 0 ,0
Exp/Cntr=0.3,0.1

Type RM Length L Ch R = 1 ,5125.7  ,228.9,211.8,194.7
XS GIS Cut Line= 4
     1709103.016      221407.155     1709226.568      221328.906
     1709365.221      221239.673     1709561.532      221088.665
#Sta/Elev= 30
     9.7 1088.01      78 1045.58    87.7 1037.19    97.5 1030.24   146.2 1004.41
   155.9 1000.86   165.6   996.1   175.3  986.89     185  980.18  196.03  974.93
   204.4  973.13   214.1  973.79  218.18  974.71   243.2  980.61   252.9  983.35
   262.6  986.74   311.1   997.6   330.9 1000.98   360.7 1010.59   370.6  1014.6
   400.3 1029.14   420.1 1039.51   439.9 1053.69   459.7 1064.27   469.6 1068.25
   479.5 1071.24   489.5 1076.48   509.3 1087.71   529.1 1103.62   558.8 1118.54
#Mann= 3 , 0 , 0
     9.7      .1       0  196.03    .045       0  218.18      .1       0
Bank Sta=196.03,218.18
XS Rating Curve= 0 ,0
Exp/Cntr=0.3,0.1

Type RM Length L Ch R = 1 ,4913.9  ,222.1,230.1,238.2
XS GIS Cut Line= 4
     1709377.348      221615.814     1709414.642      221499.133
       1709472.3      221323.414     1709567.023      221106.512
#Sta/Elev= 30
     9.4 1022.54    47.1 1008.25      66 1001.93    75.4 1001.29    84.8  999.28
   122.5  988.26   171.2   976.2   180.9  975.25   190.6  973.26   200.1  970.52
   210.1   968.8   220.1  969.59   229.6  973.06   239.3  977.98     249  981.95
   278.2  993.21     288  994.74   297.7  998.69   317.3 1009.38   376.5 1035.57
   386.3 1037.94   396.2 1041.38   406.1 1046.46   435.6 1064.28   465.2 1079.61
   475.1 1088.91   484.9 1094.77   504.7 1100.96   524.4 1109.49   544.1  1117.4
#Mann= 3 , 0 , 0
       0      .1       0   200.1    .045       0   220.1      .1       0
Bank Sta=200.1,220.1
XS Rating Curve= 0 ,0
Exp/Cntr=0.3,0.1

Type RM Length L Ch R = 1 ,4683.8  ,90.1,105.3,120.4
XS GIS Cut Line= 4
     1709491.519      221739.373     1709597.225      221588.365
     1709700.185      221449.712     1709748.233      221258.893
#Sta/Elev= 30
     9.7 1055.02    19.4 1046.42    29.1 1039.24    38.8 1034.14    48.5 1030.23
    77.6    1020      97 1016.26   126.1 1006.17   145.5  997.77   155.2   994.3
   203.5  978.07   213.1  976.66   222.7  974.26   241.5  966.58   251.5  963.85
   261.5  966.51   280.3  977.82   309.1  993.56   318.7  998.31   328.2  999.38
   337.8 1002.81   376.7 1020.61   386.5 1026.36   425.9 1047.18   435.7 1049.16
   445.6 1052.22   484.9 1072.51   534.1 1096.73     544 1096.58   553.8 1101.51
#Mann= 3 , 0 , 0
       0      .1       0   241.5    .045       0   261.5      .1       0
Bank Sta=241.5,261.5
XS Rating Curve= 0 ,0
Exp/Cntr=0.3,0.1

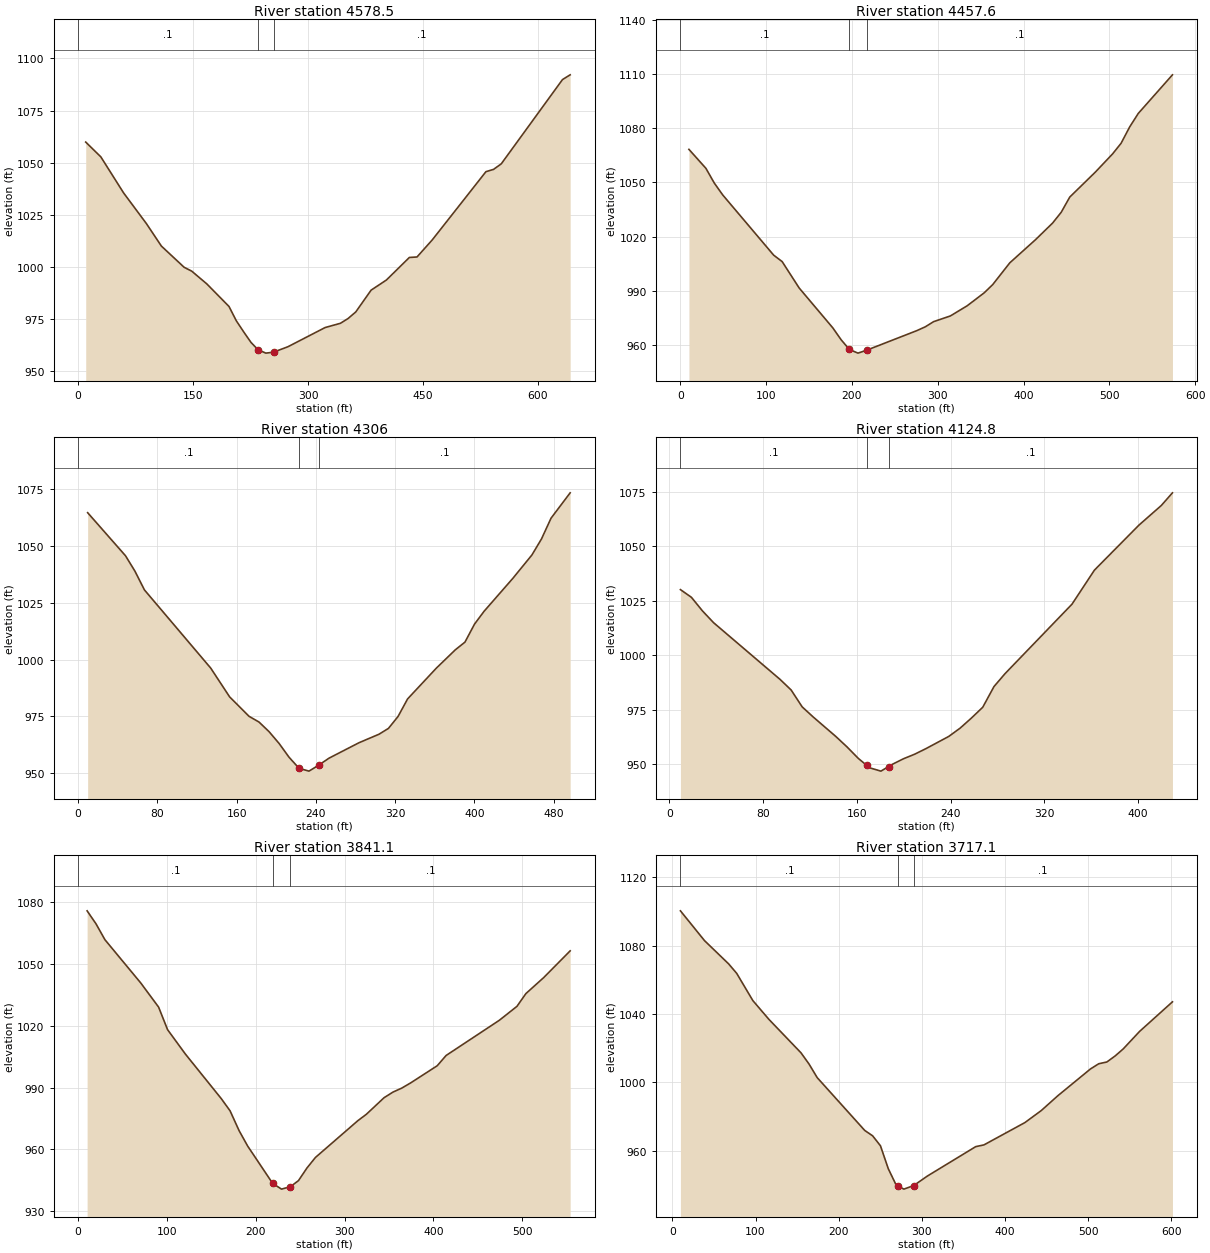
Type RM Length L Ch R = 1 ,4578.5  ,125.1,120.9,116.7
XS GIS Cut Line= 4
     1709526.297      221787.415     1709618.961      221647.389
     1709755.554      221600.714     1709787.129      221272.614
#Sta/Elev= 30
     9.9 1059.83    29.6 1052.72    59.3  1035.4    88.9 1020.73   108.6 1009.85
   138.3  999.65   148.2   997.8   167.9  991.66   196.8  980.83   206.4  973.92
     216   968.6   225.6  963.51   234.9  959.97   244.9   958.4   254.9  958.85
   273.8  961.49   322.2  970.69   342.2  972.74   352.2  975.04   362.2   978.2
   382.2  988.66   402.2  993.55   432.1 1004.37   442.1 1004.61   462.1 1012.87
     532  1045.6     542 1046.72     552 1049.37   631.9 1089.87   641.9 1092.15
#Mann= 3 , 0 , 0
       0      .1       0   234.9    .045       0   254.9      .1       0
Bank Sta=234.9,254.9
XS Rating Curve= 0 ,0
Exp/Cntr=0.3,0.1

Type RM Length L Ch R = 1 ,4457.6  ,155.5,151.6,147.7
XS GIS Cut Line= 4
     1709561.532      221849.197     1709672.728      221766.829
     1709853.938       221669.36     1710083.196       221678.97
#Sta/Elev= 30
     9.9 1068.26    29.7 1057.78    39.5 1049.61    49.4 1043.01   108.7 1009.78
   118.6 1006.22   138.4  991.65   177.6  969.62   187.4  962.98     197  957.64
     207  955.63     217  957.23   275.6  968.06   285.4  970.16   295.2  973.03
   314.7  976.18   334.3   981.8   354.1  988.95   364.1  993.53     384 1005.55
     414 1018.35   433.9 1027.53   443.9 1033.47   453.9 1041.89   483.8 1055.73
   503.8 1065.74   513.7 1071.61   523.7 1080.63   533.7 1088.08   573.6 1109.45
#Mann= 3 , 0 , 0
       0      .1       0     197    .045       0     217      .1       0
Bank Sta=197,217
XS Rating Curve= 0 ,0
Exp/Cntr=0.3,0.1

Type RM Length L Ch R = 1 ,4306    ,174.5,181.2,188
XS GIS Cut Line= 4
     1709621.935      221982.359     1709761.961      221899.991
      1709874.53      221814.877     1710063.977      221777.811
#Sta/Elev= 30
     9.6 1064.71    47.8 1045.75    57.3 1038.99    66.9 1030.71   133.8  996.28
   152.9   983.6   172.5  975.04   182.6   972.5   192.7  968.28   202.8   963.1
   212.9     957     223  952.13     233   950.9     243  953.58   253.2  956.61
   283.4  963.39   303.6  967.14   313.2  969.72   322.9  974.98   332.5  982.69
   361.5  996.24   380.8 1004.37   390.4  1007.7   400.1 1015.67   409.8 1021.34
   438.7 1035.77     458  1046.1   467.7 1053.19   477.3 1062.29   496.6 1073.46
#Mann= 3 , 0 , 0
       0      .1       0     223    .045       0     243      .1       0
Bank Sta=223,243
XS Rating Curve= 0 ,0
Exp/Cntr=0.3,0.1

Type RM Length L Ch R = 1 ,4124.8  ,284.3,283.6,283
XS GIS Cut Line= 4
     1709741.369      222104.538     1709855.311      222037.271
     1709989.845      221983.731     1710125.753      221915.091
#Sta/Elev= 30
     9.5 1030.08    18.9 1026.54    28.4 1020.27    37.8 1014.93    94.5  988.98
     104   984.1   113.4  976.39   122.9  971.71     142  962.89   151.6  958.09
   161.3  952.79  168.43  949.62   170.9  948.49   180.6  946.96  187.11  949.03
   190.2  950.04   199.9  952.63   209.5  954.73   219.2  957.31   238.5  962.85
   248.2  966.65   257.8  971.24   267.5  976.21   277.1  985.69   286.6  991.64
   343.7 1023.43   362.8 1038.99   400.8 1059.61   419.9 1068.61   429.4  1074.4
#Mann= 3 , 0 , 0
     9.5      .1       0  168.43    .045       0  187.11      .1       0
Bank Sta=168.43,187.11
XS Rating Curve= 0 ,0
Exp/Cntr=0.3,0.1

Type RM Length L Ch R = 1 ,3841.1  ,133.7,124,114.4
XS GIS Cut Line= 4
     1709763.333       222355.76     1709937.679      222306.339
     1710069.468      222250.055     1710280.879      222160.823
#Sta/Elev= 30
    10.1 1075.73    20.1 1069.43    30.2  1061.7    70.5 1040.73    90.6 1029.02
   100.7 1018.07   120.8 1006.21   161.1  984.64   171.1  978.67   181.2   969.1
   190.8  961.65     219  943.49     229   940.7     239  941.89   248.1  944.83
   257.6  950.93   267.2  956.07     315  973.93   324.5     977   344.5  985.07
   354.5  987.78   364.4  989.72   374.4  992.24   404.3 1000.56   414.3 1005.54
   474.2 1022.61   494.1 1029.39   504.1 1035.55   524.1  1043.3     554 1056.31
#Mann= 3 , 0 , 0
       0      .1       0     219    .045       0     239      .1       0
Bank Sta=219,239
XS Rating Curve= 0 ,0
Exp/Cntr=0.3,0.1

Type RM Length L Ch R = 1 ,3717.1  ,185.6,177.3,169
XS GIS Cut Line= 4
     1709798.111      222543.828     1709979.321       222451.85
     1710065.807      222365.363     1710268.982      222178.663
#Sta/Elev= 30
     9.7  1100.4    38.7 1082.94    67.7 1069.34    77.4 1063.78    96.8 1047.86
   116.1 1036.87   154.8 1017.23   164.5 1010.63   174.2 1002.76   231.4  971.82
   240.9  968.67   250.3  962.83   259.7  949.43   269.1  939.94  271.89  939.17
   278.5  937.47  290.39  939.59   306.7  945.12   364.9  962.35   374.8  963.37
   424.1  976.45   443.8   983.5   463.5  992.09   502.9 1007.83   512.8 1010.86
   522.6  1011.9   532.5 1015.41   542.3 1019.56     562 1029.81   601.5 1047.12
#Mann= 3 , 0 , 0
     9.7      .1       0  271.89    .045       0  290.39      .1       0
Bank Sta=271.89,290.39
XS Rating Curve= 0 ,0
Exp/Cntr=0.3,0.1

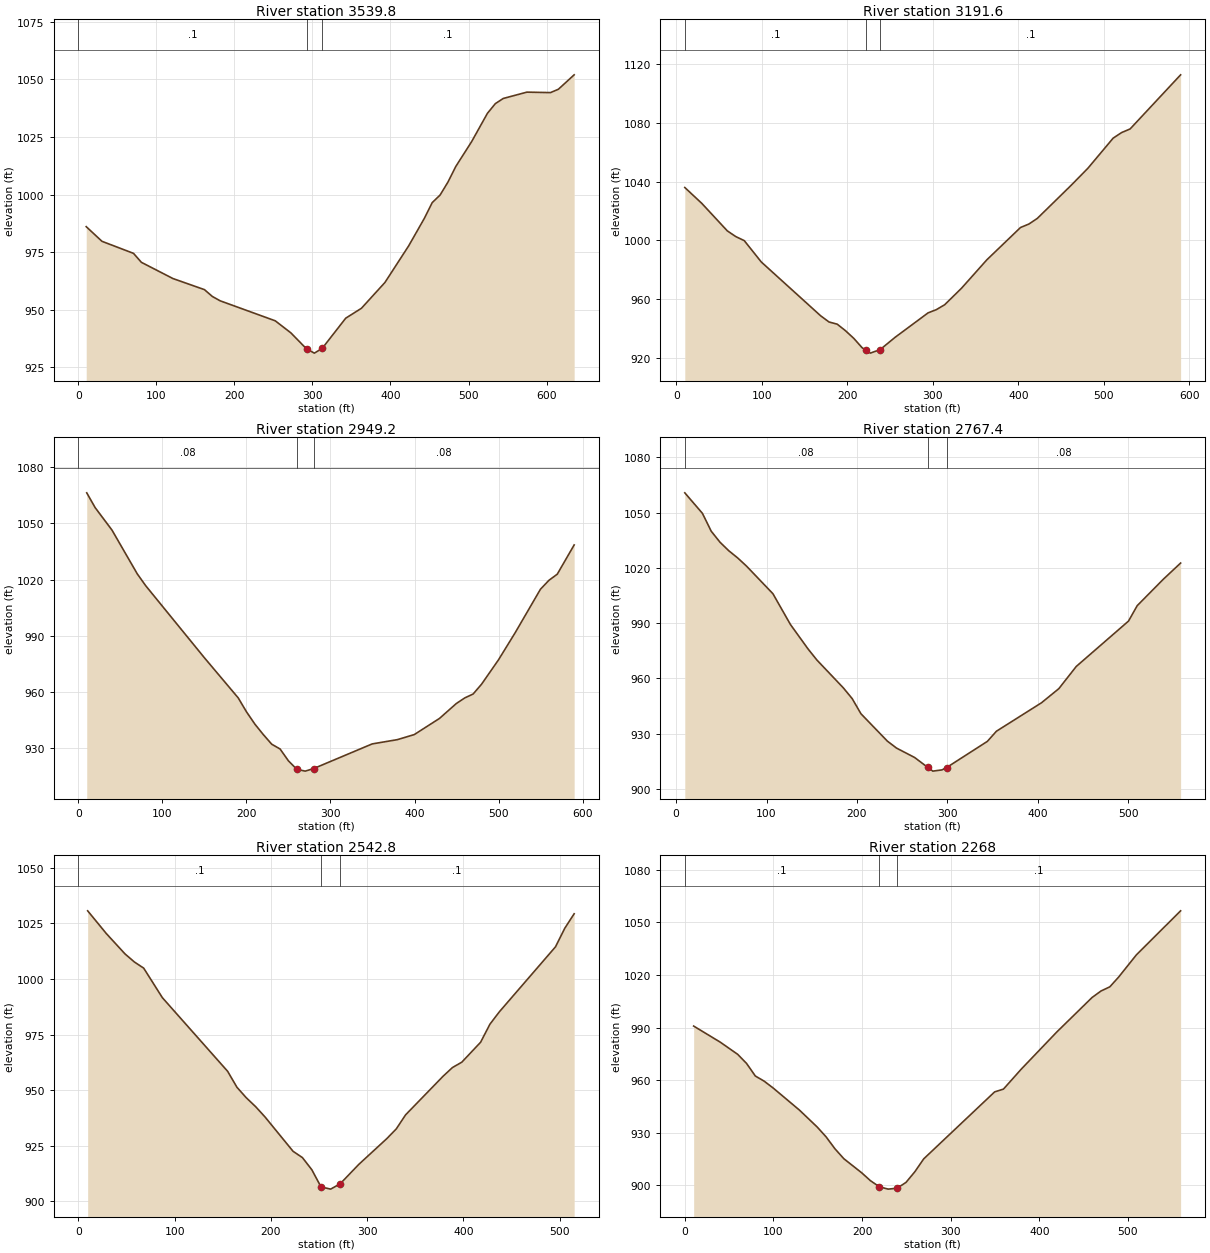
Type RM Length L Ch R = 1 ,3539.8  ,343.2,348.2,353.2
XS GIS Cut Line= 4
     1709981.609      222715.434     1710140.854      222575.408
     1710224.594      222403.808     1710282.252      222178.669
#Sta/Elev= 30
    10.1  986.07    30.3   979.7    70.7  974.47    80.8  970.58   121.2  963.54
   161.6  958.72   171.7  955.76   181.8  953.86   252.3  945.19   272.3  939.97
   292.5  932.98   302.5  931.15   312.5  933.21   342.7  946.33   362.8  950.62
   392.9  961.82   423.2  977.65   443.4  989.65   453.5   996.5   463.6  999.79
   473.7 1005.44   483.8 1012.25     504 1022.97   524.2 1035.25   534.4 1039.48
   544.5 1041.72   574.8 1044.47   605.1 1044.27   615.2 1045.73   635.4 1051.99
#Mann= 3 , 0 , 0
       0      .1       0   292.5    .045       0   312.5      .1       0
Bank Sta=292.5,312.5
XS Rating Curve= 0 ,0
Exp/Cntr=0.3,0.1

Type RM Length L Ch R = 1 ,3191.6  ,241.4,242.4,243.5
XS GIS Cut Line= 4
     1710325.267      222939.194     1710392.076      222784.074
     1710479.935      222668.759     1710594.335       222417.53
#Sta/Elev= 30
     9.9 1035.98    29.8  1025.2    59.6 1006.54    69.5 1002.67    79.5  999.87
    99.4  985.37   168.9   948.8   178.6  944.64   188.2  943.15   197.9  938.69
   207.6  933.49   217.2  927.23  221.64  925.47   226.9  923.48  238.35  925.85
   255.9  934.21   294.5  950.83   304.2  953.03   313.9  956.35   333.6  967.56
   363.2  986.84   402.6 1008.81   412.5 1011.19   422.3 1015.01   461.8 1037.45
   481.5  1049.1     511 1069.52   520.9 1073.31   530.8 1075.74   589.9 1112.52
#Mann= 3 , 0 , 0
     9.9      .1       0  221.64    .045       0  238.35      .1       0
Bank Sta=221.64,238.35
XS Rating Curve= 0 ,0
Exp/Cntr=0.3,0.1

Type RM Length L Ch R = 1 ,2949.2  ,167,181.8,196.6
XS GIS Cut Line= 4
     1710439.209      223055.882     1710587.471      222921.348
     1710676.703      222814.269     1710736.649       222571.29
#Sta/Elev= 30
      10 1066.19      20 1058.31      40 1046.36    70.1 1023.02    80.1 1016.72
   150.2  978.18   190.2  956.92   200.2  949.39   210.2  942.84   220.1  937.35
   230.1  932.22     240  929.69     250  923.35   259.9  918.86   269.9  917.88
   279.9  919.24   349.6  932.38   379.6  934.66   399.7  937.36   429.7  945.97
   449.7   953.9   459.7  956.87   469.7  958.98   479.7  964.18   499.8  977.13
   519.8  991.69   549.8 1014.81   559.8 1019.53   569.8 1022.83   589.9 1038.42
#Mann= 3 , 0 , 0
       0     .08       0   259.9    .045       0   279.9     .08       0
Bank Sta=259.9,279.9
XS Rating Curve= 0 ,0
Exp/Cntr=0.3,0.1

Type RM Length L Ch R = 1 ,2767.4  ,233.3,224.6,215.8
XS GIS Cut Line= 4
     1710503.731      223128.641     1710706.905      223013.325
     1710860.659       222966.65     1711021.276      222936.449
#Sta/Elev= 30
     9.7 1060.74    29.2 1049.59    38.9  1039.9    48.7 1033.87    58.4 1029.25
    68.1 1025.41    77.9 1020.95   107.1 1005.95   126.5   989.2     146  975.91
   155.7  969.95   184.9  954.83   194.7  948.99   204.4  940.76   233.6   925.9
   243.7  922.12   263.7  917.02  278.14  911.67   283.8  909.61   293.9  910.27
  299.01  911.54   344.1  925.76   354.1  931.27   403.9  946.72   423.1   954.4
   442.4  966.47   500.1  991.09   509.7  999.45   538.5 1013.78   557.7 1022.61
#Mann= 3 , 0 , 0
     9.7     .08       0  278.14    .045       0  299.01     .08       0
Bank Sta=278.14,299.01
XS Rating Curve= 0 ,0
Exp/Cntr=0.3,0.1

Type RM Length L Ch R = 1 ,2542.8  ,276.7,274.8,272.9
XS GIS Cut Line= 4
     1710630.028      223342.798     1710811.238      223230.228
     1710921.062      223149.233      1711072.07      223081.965
#Sta/Elev= 30
     9.7  1030.7    29.1 1020.45    48.5 1011.29    58.2 1007.67    67.9 1004.89
    87.3  991.59   155.1  958.43   164.8  951.22   174.5   946.5   184.2   942.5
   193.9  937.89   223.1  922.39   232.8  919.56   242.6  914.07   252.1  906.37
   262.1  905.36   272.1  907.79   291.3  916.47   320.5  928.12   330.3  932.48
     340  938.82     379  956.23   388.7  960.13   398.4  962.54   417.9   971.5
   427.6  979.64   437.3  985.17   495.7 1014.48   505.4 1022.88   515.1 1029.37
#Mann= 3 , 0 , 0
       0      .1       0   252.1    .045       0   272.1      .1       0
Bank Sta=252.1,272.1
XS Rating Curve= 0 ,0
Exp/Cntr=0.3,0.1

Type RM Length L Ch R = 1 ,2268    ,292.4,283.5,274.6
XS GIS Cut Line= 4
     1710817.644      223595.399     1710901.385      223510.286
      1711060.63      223373.006       1711173.2      223172.577
#Sta/Elev= 30
      10  990.85    39.8  981.74    59.7  974.71    69.7  969.52    79.6  962.35
    89.6  959.39    99.5  955.58   129.4  942.88   149.4  933.23   159.4  927.64
   169.5  920.77   179.5  915.12   199.5  907.15   209.5   902.6   219.5  899.13
   229.5  897.78   239.5   898.3   249.6  901.61   259.6  907.71   269.6  915.05
   349.6  953.27   359.6  954.88   379.6  966.23   419.6  987.38   459.6 1007.17
   469.6 1010.85   479.6 1013.25   489.6 1018.84   509.6 1031.51   559.5 1056.63
#Mann= 3 , 0 , 0
       0      .1       0   219.5    .045       0   239.5      .1       0
Bank Sta=219.5,239.5
XS Rating Curve= 0 ,0
Exp/Cntr=0.3,0.1

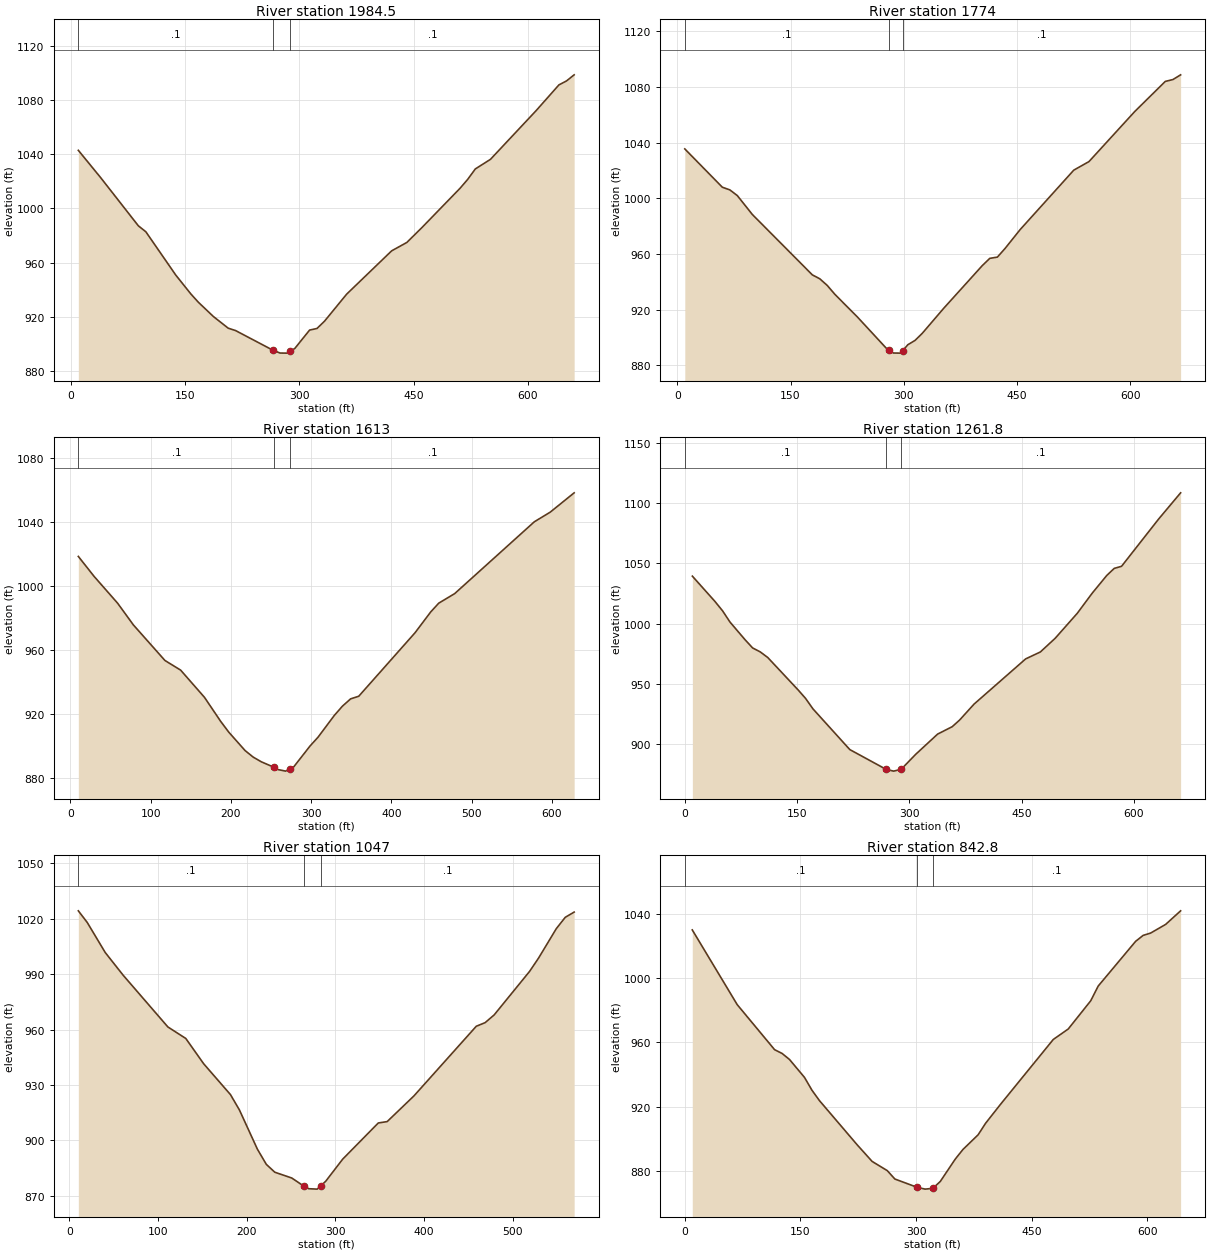
Type RM Length L Ch R = 1 ,1984.5  ,210.2,210.5,210.7
XS GIS Cut Line= 4
     1711057.884      223841.131     1711166.336       223688.75
     1711265.177      223510.286     1711362.646      223259.063
#Sta/Elev= 30
     9.8 1042.73    39.4 1022.39    88.6  987.06    98.4  982.69   137.8  950.67
   157.5  936.83   167.3  930.75     187  920.24   206.5  911.61   216.2  909.84
   264.8  895.48   274.5  893.28   284.2  893.22  288.08   894.6   293.9  896.67
   313.3  910.21     323  911.39   332.8  916.71   361.9  936.67     421  968.63
   440.9   974.8   460.9  985.89   510.8 1014.78   520.8 1021.32   530.8 1029.01
   550.7  1036.1   610.6    1072   640.5 1090.96   650.5  1093.9   660.5 1098.39
#Mann= 3 , 0 , 0
     9.8      .1       0   264.8    .045       0  288.08      .1       0
Bank Sta=264.8,288.08
XS Rating Curve= 0 ,0
Exp/Cntr=0.3,0.1

Type RM Length L Ch R = 1 ,1774    ,160.6,161,161.4
XS GIS Cut Line= 4
     1711213.999       223927.49     1711372.558      223749.369
     1711429.186      223649.498     1711590.833      223380.772
#Sta/Elev= 30
     9.9 1035.44    59.6 1007.95    69.6 1006.02    79.5 1001.93    99.4  988.37
   178.9  945.02   188.8   942.2   198.7  937.41   208.7  931.09   238.5  914.85
   276.7  892.48  280.98  890.84   286.3  888.92   295.9  888.84  298.58  890.51
   305.4  894.85     315  897.97   324.6  903.07   353.3  921.22   403.9  951.55
     414  956.86   424.1  957.78   434.2  963.93   454.4   977.6   525.3 1020.18
   545.5 1026.35   606.2 1062.33   646.6 1083.89   656.8 1085.25   666.9 1088.62
#Mann= 3 , 0 , 0
     9.9      .1       0  280.98    .045       0  298.58      .1       0
Bank Sta=280.98,298.58
XS Rating Curve= 0 ,0
Exp/Cntr=0.3,0.1

Type RM Length L Ch R = 1 ,1613    ,347.9,351.3,354.7
XS GIS Cut Line= 4
     1711395.593      224003.121     1711484.825      223874.078
     1711602.886      223673.649      1711722.32      223467.729
#Sta/Elev= 30
     9.8 1018.64    29.4 1006.17    58.8  989.32    78.4  975.75   117.7  953.49
   137.3  947.43     167  930.39   187.2  915.33   197.3  908.57   217.6  897.05
   227.7  892.97   237.8  890.03  253.88  886.54     258  885.22   268.1  884.19
  273.98  885.76   278.3  886.92   298.5  899.92   308.6  905.52   328.8  919.09
   338.9  924.88   349.1  929.45   359.2  931.08   429.2  970.76     449  983.96
   458.9  989.38   478.8  995.38     578 1040.34   597.8 1046.37   627.6 1058.47
#Mann= 3 , 0 , 0
     9.8      .1       0  253.88    .045       0  273.98      .1       0
Bank Sta=253.88,273.98
XS Rating Curve= 0 ,0
Exp/Cntr=0.3,0.1

Type RM Length L Ch R = 1 ,1261.8  ,220.1,214.8,209.5
XS GIS Cut Line= 4
      1711644.07      224207.668     1711759.386      224067.643
     1711904.902      223883.687     1712002.371      223657.175
#Sta/Elev= 30
    10.1 1039.44    40.3 1018.39    50.4 1010.62    60.5 1001.15    80.6  986.47
    90.7  979.65   100.8  976.41   110.9   971.7   151.2  944.89   161.2  937.83
   171.3  928.94   220.5  895.09   269.1  878.61   279.1  877.17   289.1  878.68
   308.4  891.08   337.8  907.98   357.3  914.15   367.1  919.62   386.6     933
   455.4  970.55   475.1  976.34   494.9  987.74   524.4 1008.51   544.2 1025.13
   563.9 1040.07   573.8 1045.89   583.6 1047.65     633 1086.87   662.5 1108.78
#Mann= 3 , 0 , 0
       0      .1       0   269.1    .045       0   289.1      .1       0
Bank Sta=269.1,289.1
XS Rating Curve= 0 ,0
Exp/Cntr=0.3,0.1

Type RM Length L Ch R = 1 ,1047    ,198.8,204.1,209.5
XS GIS Cut Line= 4
     1711822.493        224338.3     1711965.608      224168.416
     1712003.703      224091.196     1712117.988      223856.447
#Sta/Elev= 30
    10.1 1024.24    20.2  1017.9    40.4  1001.7    60.6  989.42   111.1  961.38
   131.3  955.15   151.5  941.44   181.7  924.75   191.8  916.44     212  895.28
   222.1  887.02   231.7  882.75   250.8  879.62  264.51   875.2     270  873.82
   279.5   873.6   283.6   875.4   289.1  877.86   308.2   889.8   348.4  909.41
   358.4  910.15   388.6  924.05   458.9  961.75   468.9  963.72     479  967.85
   519.1   991.5   529.2  998.69   549.2 1014.61   559.3 1020.74   569.3 1023.56
#Mann= 3 , 0 , 0
    10.1      .1       0  264.51    .045       0   283.6      .1       0
Bank Sta=264.51,283.6
XS Rating Curve= 0 ,0
Exp/Cntr=0.3,0.1

Type RM Length L Ch R = 1 ,842.8   ,232.5,231.5,230.6
XS GIS Cut Line= 4
     1711968.051      224460.264     1712103.958      224295.528
     1712226.138      224141.774      1712315.37      223926.244
#Sta/Elev= 30
     9.7 1029.95      68  983.44   116.5  955.41   126.2  953.07   135.9  949.29
   155.3  938.15     165  930.15   174.7  923.71   223.4  896.33     243  885.87
   262.7  880.13   272.5  874.92   301.8   869.7   311.8  868.63   321.8  869.12
   331.4  873.39     351  887.41   360.9  893.34   380.5  902.44   390.3  909.68
   409.9  921.61     478  961.77   497.4  968.28   526.6  985.86   536.3  995.02
   584.9 1022.88   594.6 1026.54   604.3 1027.99   623.8 1033.39   643.2 1041.83
#Mann= 3 , 0 , 0
       0      .1       0   301.8    .045       0   321.8      .1       0
Bank Sta=301.8,321.8
XS Rating Curve= 0 ,0
Exp/Cntr=0.3,0.1