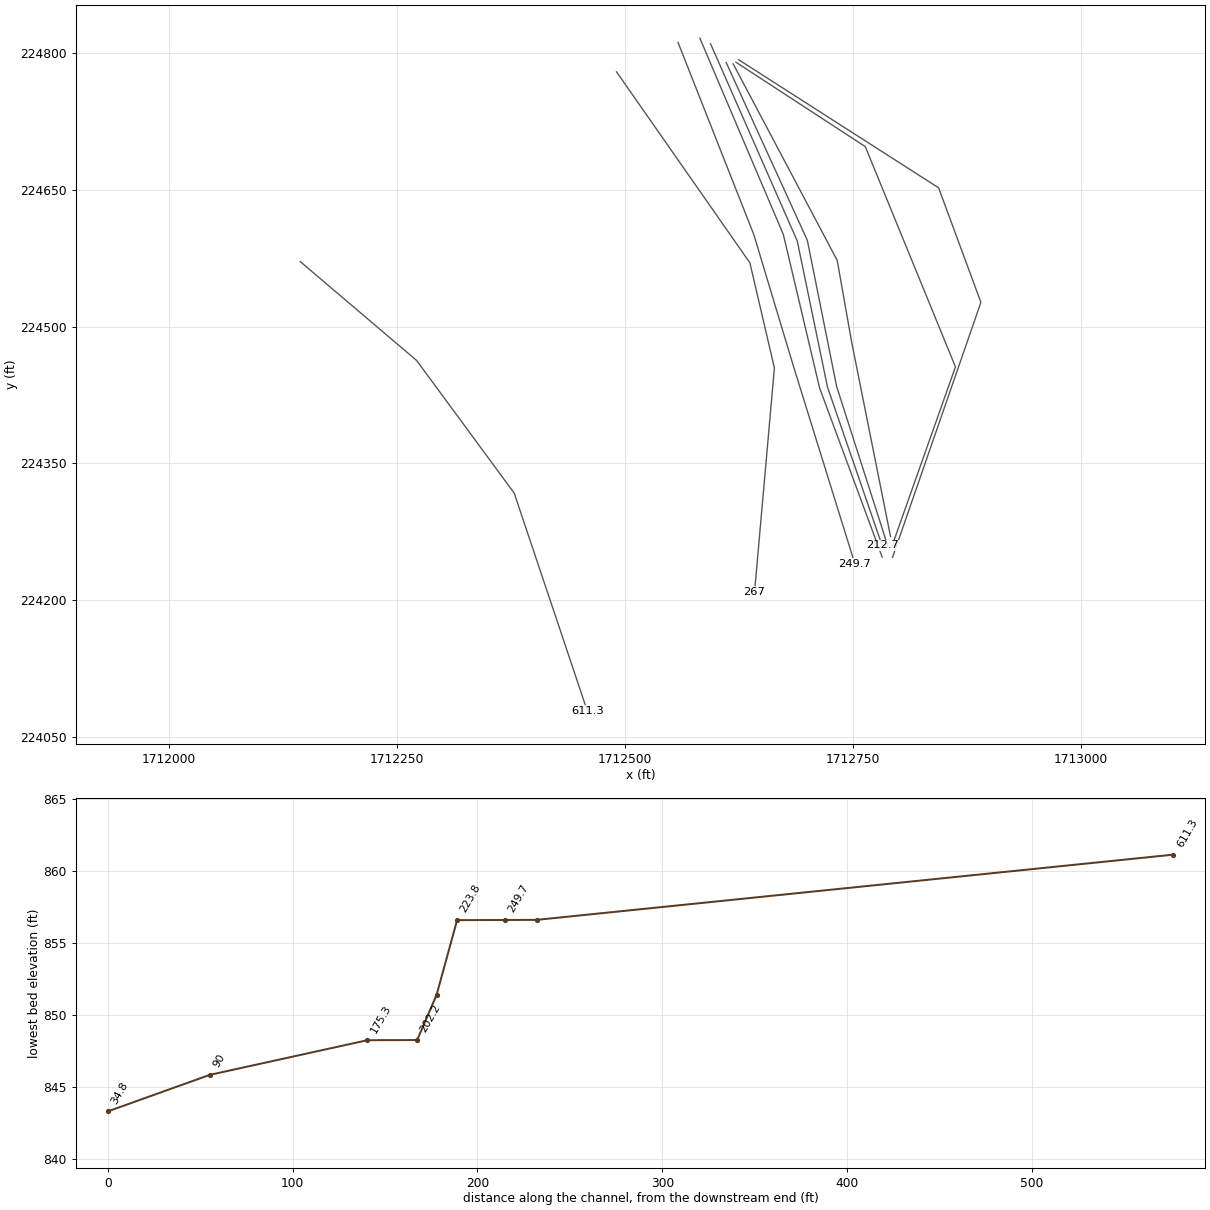
HEC-RAS study sklltcrk.prj: sklltcrk

--- sklltcrk.g01 (geometry) --- (continued)

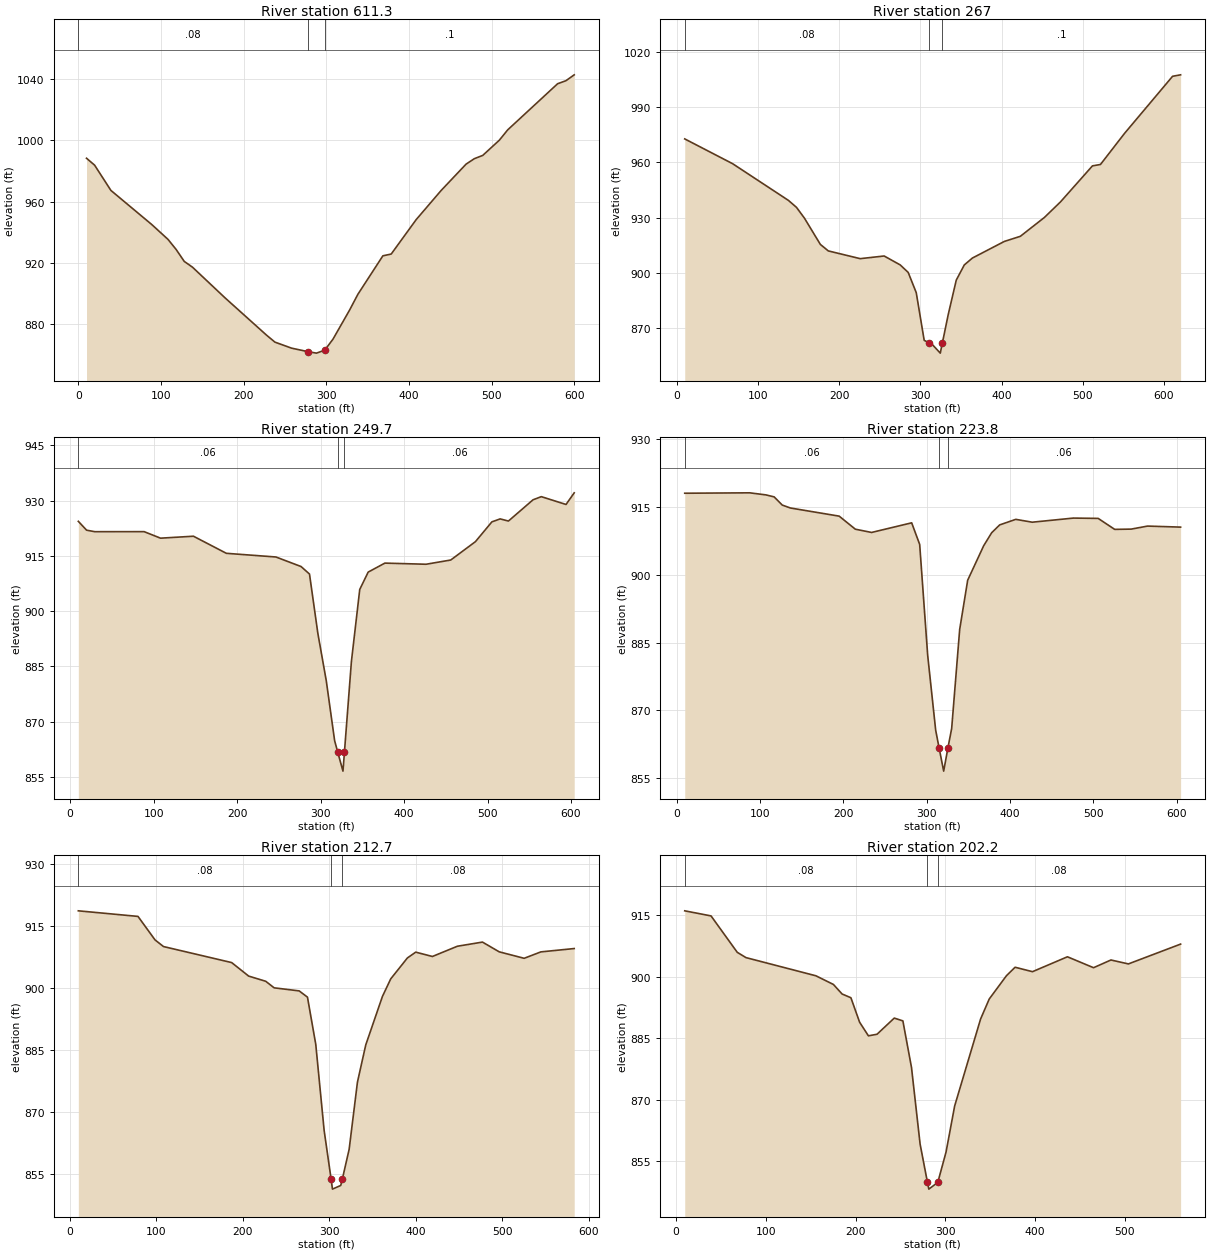
Type RM Length L Ch R = 1 ,611.3   ,354.5,344.3,334.1
XS GIS Cut Line= 4
      1712143.77      224571.461      1712271.44      224463.009
     1712378.519      224317.492     1712458.552       224079.01
#Sta/Elev= 30
     9.9  988.23    19.7  983.71    39.4  967.24    88.7  945.04   108.4  935.34
   118.2  928.79   128.1  920.94     138   917.2   177.6  897.08   227.7   872.8
   237.8  868.28   257.8  864.38     278  862.04     288  861.12     298  863.05
     308  870.26   328.1  889.26   338.1  899.51   368.3  924.58   378.4  925.76
   408.6  948.21   438.7  967.17   468.9  984.38     479  987.97   489.1  990.09
   509.2 1000.03   519.2 1006.71   579.6 1036.82   589.7  1038.8   599.7 1042.64
#Mann= 3 , 0 , 0
       0     .08       0     278    .045       0     298      .1       0
Bank Sta=278,298
XS Rating Curve= 0 ,0
Exp/Cntr=0.3,0.1

Type RM Length L Ch R = 1 ,267     ,15.6,17.2,18.8
XS GIS Cut Line= 4
     1712490.745       224779.44     1712636.988      224570.046
     1712663.864      224454.723     1712642.096      224209.041
#Sta/Elev= 30
     9.8  972.74    68.8  959.29   137.5   939.4   147.4  935.64   157.2  929.79
   176.8  915.55   186.6  912.01   225.9  907.81   255.4  909.25   275.1  904.44
     285  900.35   294.9  889.39   304.7  863.52  310.08  862.33   314.6  861.31
   324.5  856.59  326.99  861.88   334.3   877.5   344.2  896.17   354.1  904.41
     364  908.12   403.4  917.15   423.1  919.92   452.7  930.13   472.5  938.56
   511.9  958.11   521.8  958.88   551.4  975.71   610.6 1006.69   620.5 1007.48
#Mann= 3 , 0 , 0
     9.8     .08       0  310.08    .045       0  326.99      .1       0
Bank Sta=310.08,326.99
XS Rating Curve= 0 ,0
Exp/Cntr=0.3,0.1

Type RM Length L Ch R = 1 ,249.7   ,27.5,25.9,24.4
XS GIS Cut Line= 4
     1712558.184      224811.744      1712641.26      224601.099
     1712684.696       224456.89     1712752.006      224240.315
#Sta/Elev= 30
     9.8  924.39    19.7  921.99    29.5  921.58    88.6  921.59   108.3  919.82
   147.7  920.35   187.1  915.71   246.5  914.71   276.6  912.12   286.7  910.08
   296.7     894   306.8  881.12   316.8  864.86  320.53  861.72   326.8  856.58
  328.55  861.72   336.9  886.33   346.9   905.9     357  910.61     377  913.05
   426.3  912.74   455.9  913.89   485.5  918.88   505.2  924.25   515.1  925.05
     525  924.47   554.5  930.24   564.4  931.09     594  928.97   603.8  932.13
#Mann= 3 , 0 , 0
     9.8     .06       0  320.53    .045       0  328.55     .06       0
Bank Sta=320.53,328.55
XS Rating Curve= 0 ,0
Exp/Cntr=0.3,0.1

Type RM Length L Ch R = 1 ,223.8   ,11.8,11.1,10.4
XS GIS Cut Line= 4
     1712582.122      224816.377     1712673.692      224601.099
     1712713.432      224432.812     1712782.122      224247.265
#Sta/Elev= 30
     9.7  918.07    87.7  918.16   107.2   917.7     117  917.26   126.7  915.45
   136.5   914.8     195     913   214.4  910.11   233.9  909.39     282  911.52
   291.6  906.74   301.2  882.22   310.8  865.63  314.94  861.67   320.4  856.57
  325.38   861.6     330  866.02   339.6  887.92   349.2  898.82   368.4  906.45
     378  909.33   387.6  911.06   406.9  912.29   426.6  911.66   476.1  912.57
   505.8   912.5   525.6  910.07   545.4  910.13   565.1   910.8   604.7  910.57
#Mann= 3 , 0 , 0
     9.7     .06       0  314.94    .045       0  325.38     .06       0
Bank Sta=314.94,325.38
XS Rating Curve= 0 ,0
Exp/Cntr=0.3,0.1

Type RM Length L Ch R = 1 ,212.7   ,10.7,10.5,10.4
XS GIS Cut Line= 4
     1712593.837      224810.273     1712688.963       224593.96
     1712722.119      224433.681     1712781.916       224260.37
#Sta/Elev= 30
     9.8  918.67    78.8  917.32    98.5  911.64   108.3  910.03   187.1  906.16
   206.8  902.89   226.5  901.64   236.3  900.05   265.2  899.31   274.8   897.8
   284.4  886.38   294.1  865.54   302.1  853.88   303.7  851.38   313.3  852.27
  315.15  853.83     323     861   332.6  877.25   342.2  886.24   361.5  897.97
   371.1  902.22   390.4  907.28     400  908.68   419.3  907.63   448.2  910.11
   477.2  911.11   496.5  908.76   525.4  907.19   544.7  908.74   583.3  909.55
#Mann= 3 , 0 , 0
     9.8     .08       0   302.1    .045       0  315.15     .08       0
Bank Sta=302.1,315.15
XS Rating Curve= 0 ,0
Exp/Cntr=0.3,0.1

Type RM Length L Ch R = 1 ,202.2   ,27.5,26.9,26.3
XS GIS Cut Line= 4
     1712610.979       224789.73     1712699.967      224594.829
      1712732.11      224434.549     1712788.414       224258.97
#Sta/Elev= 30
     9.7  916.06      39  914.82    68.2  905.95    77.9  904.66   155.8  900.23
   175.3  898.12     185  895.79   194.8  894.88   204.5  888.92   214.3   885.6
   223.9  885.98   243.1  889.92   252.7  889.24   262.3   877.9   271.9  859.21
  279.91  850.08   281.6  848.24   291.6  849.88   300.8  857.28   310.4  868.52
   339.3  889.71   348.9  894.57   368.1  900.25   377.7  902.31   397.1  901.23
     436  904.86   465.1   902.2   484.5  904.08   503.9  903.12   562.1  907.95
#Mann= 3 , 0 , 0
     9.7     .08       0  279.91    .045       0   291.6     .08       0
Bank Sta=279.91,291.6
XS Rating Curve= 0 ,0
Exp/Cntr=0.3,0.1

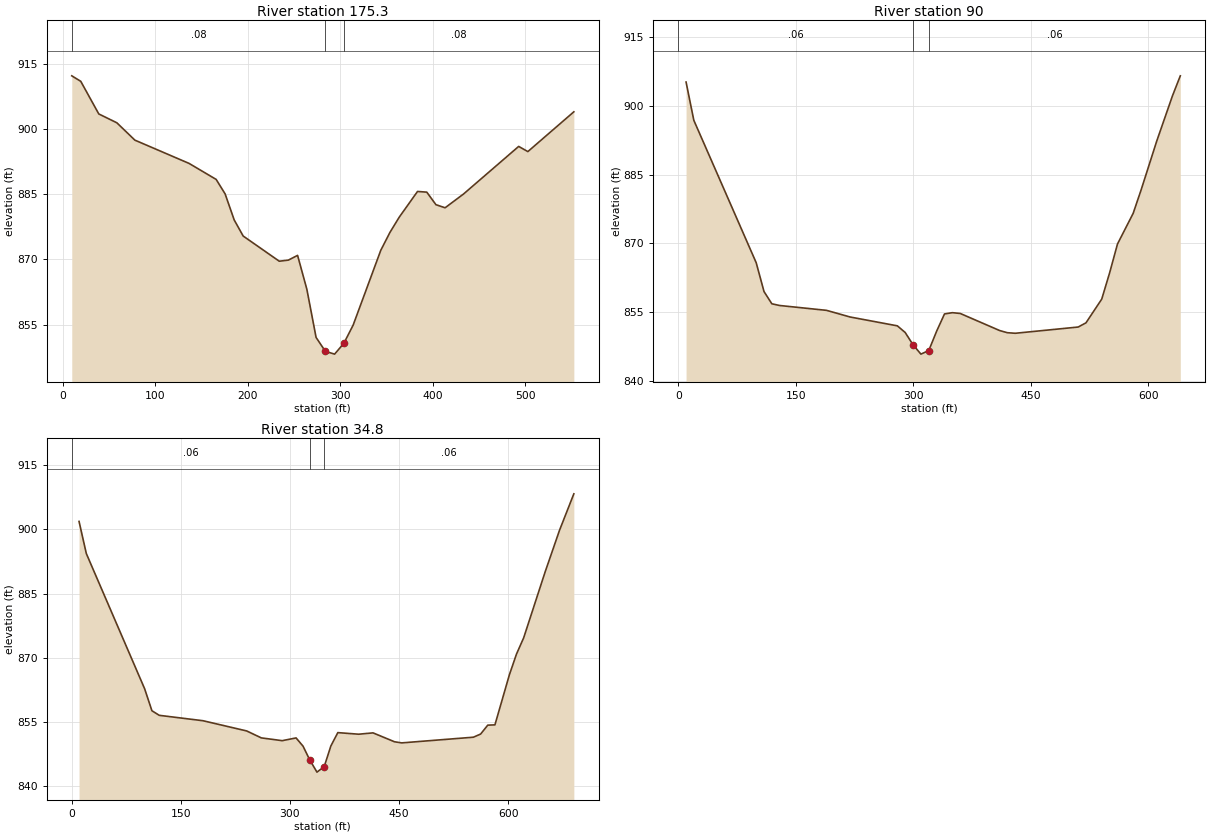
Type RM Length L Ch R = 1 ,175.3   ,79.9,85.3,90.7
XS GIS Cut Line= 4
     1712618.673      224788.164     1712732.766       224572.72
     1712748.403      224484.111      1712791.26      224269.825
#Sta/Elev= 30
     9.8  912.18    19.5  910.92      39  903.42    58.5  901.39      78   897.4
   136.5  892.06   165.8  888.38   175.5  885.05   185.3  879.07     195  875.37
     234  869.58   243.8  869.83   253.8  870.92   263.8  863.15   273.8  852.06
   283.8  848.88   293.8  848.23   303.8  850.72   313.8  854.88   343.7  872.09
   353.6   876.2   363.6  879.69   383.4  885.61   393.4  885.45   403.3  882.57
   413.2  881.86   433.1  885.02   492.7  895.96   502.6  894.77   552.3  903.91
#Mann= 3 , 0 , 0
     9.8     .08       0   283.8    .045       0   303.8     .08       0
Bank Sta=283.8,303.8
XS Rating Curve= 0 ,0
Exp/Cntr=0.3,0.1

Type RM Length L Ch R = 1 ,90      ,56,55.2,54.3
XS GIS Cut Line= 4
     1712621.801      224789.949     1712763.548      224697.502
     1712862.438      224455.924     1712792.119      224257.348
#Sta/Elev= 30
      10  905.17    19.9  896.83    99.5  865.77   109.5  859.47   119.5   856.8
   129.4  856.43   189.3  855.37   219.4  853.92   279.7  851.99   289.7  850.54
   299.8  847.84   309.8  845.82   319.8   846.6   329.9  850.84   339.9  854.59
   349.9  854.86     360  854.69   410.2  850.97   420.2  850.49   430.3  850.37
   510.5  851.73   520.5  852.65   540.6  857.82   550.6  863.51   560.7  869.84
   580.7  876.52   590.8  881.61   610.8  892.29   630.9  902.17   640.9  906.53
#Mann= 3 , 0 , 0
       0     .06       0   299.8    .045       0   319.8     .06       0
Bank Sta=299.8,319.8
XS Rating Curve= 0 ,0
Exp/Cntr=0.3,0.1

Type RM Length L Ch R = 1 ,34.8    ,40.7,34.8,29
XS GIS Cut Line= 4
     1712624.593      224792.825     1712844.012      224652.278
     1712890.344      224526.667     1712793.448      224247.136
#Sta/Elev= 30
      10  901.86      20  894.35   100.2  862.75   110.2  857.62   120.3  856.55
   180.4  855.29   240.5   852.9   260.6  851.28   289.3  850.63   308.4  851.27
     318  849.34   327.1  846.17   337.1  843.28   347.1  844.57   356.2  849.38
   365.8  852.51   394.5  852.14   414.2  852.45   443.8  850.37   453.6  850.11
   552.2  851.44   562.1  852.17     572  854.26   581.8  854.32   601.6  865.98
   611.4  870.84   621.3  874.65   650.9  890.09   670.6  899.78   690.3   908.3
#Mann= 3 , 0 , 0
       0     .06       0   327.1    .045       0   347.1     .06       0
Bank Sta=327.1,347.1
XS Rating Curve= 0 ,0
Exp/Cntr=0.3,0.1

Chan Stop Cuts=-1
Use User Specified Reach Order=0